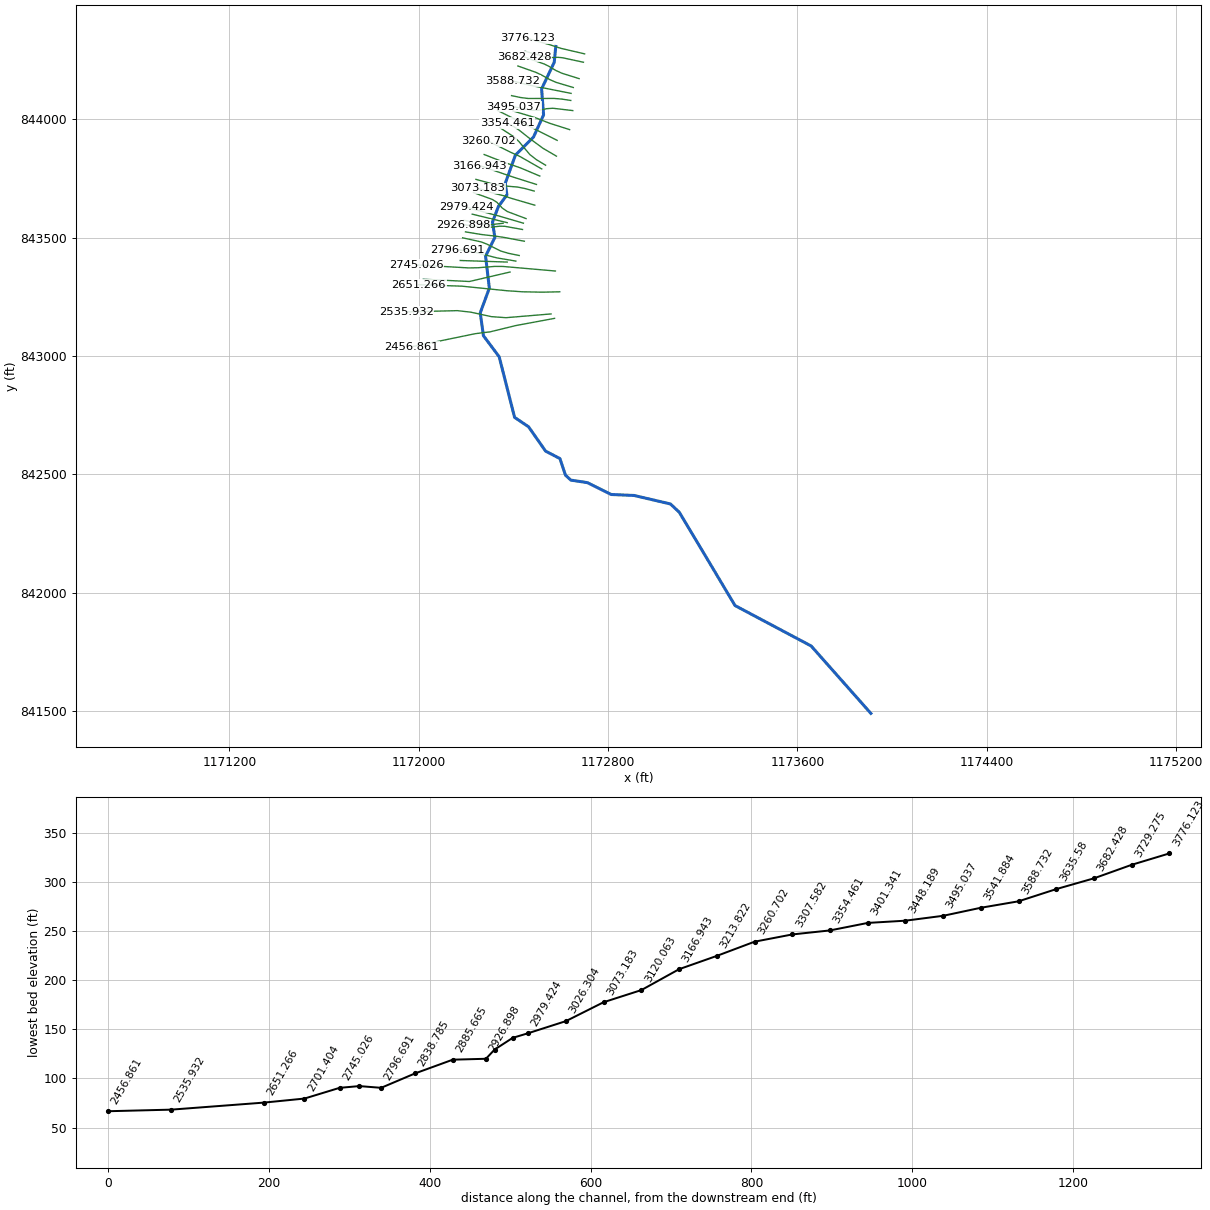
--- 87_ras.prj (project) ---

Proj Title=87
Current Plan=p01
Default Exp/Contr=0.3,0.1
English Units
Geom File=g01
Flow File=f01
Plan File=p01
Y Axis Title=Elevation
X Axis Title(PF)=Main Channel Distance
X Axis Title(XS)=Station
BEGIN DESCRIPTION:
RFD model 87 exported to HEC-RAS
END DESCRIPTION:

--- 87_ras.p01 (plan) ---

Plan Title=Plan 01
Program Version=4.10
Short Identifier=Plan 01
Geom File=g01
Flow File=f01
Subcritical Flow
Calc Critical at every XS
Secant Critical Depth

--- 87_ras.f01 (steady flow) ---

Flow Title=Flow 01
Program Version=5.01
Number of Profiles= 5
Profile Names=10yr,25yr,50yr,100yr,500yr
River Rch & RM=87,41,3776.123
  170.69  305.74  437.88  597.94 1081.26
River Rch & RM=87,41,3729.275
  175.01  313.64  449.42  614.05 1112.08
River Rch & RM=87,41, 3635.58
  179.32  321.54  460.97  630.17 1142.97
River Rch & RM=87,41,3541.884
   204.5  367.75  528.68  724.89 1325.31
River Rch & RM=87,41,3401.341
  207.56  373.38  536.95  736.48  1347.7
River Rch & RM=87,41,3307.582
  213.69  384.65  553.48  759.66 1392.57
River Rch & RM=87,41,3213.822
   219.2  394.78  568.37  780.54 1433.07
River Rch & RM=87,41,3120.063
  225.92  407.17  586.57  806.09  1482.7
River Rch & RM=87,41,2979.424
  231.42   417.3  601.47  827.01 1523.41
River Rch & RM=87,41,2885.665
  236.92  427.43  616.38  847.96 1564.22
River Rch & RM=87,41,2796.691
  242.41  437.55  631.28  868.92 1605.12
River Rch & RM=87,41,2651.266
  245.46  443.18  639.57  880.57 1627.88
River Rch & RM=87,41,2535.932
  253.99  458.93  662.77  913.22 1691.75
River Rch & RM=87,41,2360.062
  258.25   466.8  674.38  929.56 1723.76
River Rch & RM=87,41,2276.229
  305.62  554.47  803.86 1112.28 2083.79
River Rch & RM=87,41, 2182.47
  309.26   561.2  813.83 1126.38 2111.72
River Rch & RM=87,41,1994.951
  320.76  582.54  845.42 1171.07 2200.38
River Rch & RM=87,41,1901.192
  325.59  591.52  858.73  1189.9  2237.8
River Rch & RM=87,41,1763.955
  328.01  596.01  865.38 1199.32 2256.53
River Rch & RM=87,41,1590.812
  339.49  617.34  896.99  1244.1 2345.68
River Rch & RM=87,41, 1354.65
  346.74   630.8  916.96 1272.41 2402.14
River Rch & RM=87,41,1228.404
  603.95  1112.2 1635.69 2298.45 4487.91
River Rch & RM=87,41,1167.909
  605.74 1115.55 1640.72 2305.67 4502.82
Boundary for River Rch & Prof#=87,41,1
Up Type= 0
Dn Type= 2
Boundary for River Rch & Prof#=87,41,2
Up Type= 0
Dn Type= 2
Boundary for River Rch & Prof#=87,41,2
Up Type= 0
Dn Type= 2
Boundary for River Rch & Prof#=87,41,2
Up Type= 0
Dn Type= 2
Boundary for River Rch & Prof#=87,41,2
Up Type= 0
Dn Type= 2

--- 87_ras.g01 (geometry) ---

Geom Title=87
Program Version=4.10

River Reach=87,41
Reach XY= 30
1172578.97054515844307.876493232 1172572.4540207 844241.07639503
1172519.12069979844128.5764298171172527.45402749844018.576462035
1172484.95403729843925.2431574931172408.28739091843848.576515717
1172365.78739998843730.2432185561172372.45406324843680.243233121
1172336.62073904843631.9099150791172311.62074448843566.076601946
1172321.62073968843501.0766208691172282.45408221843421.909978696
  1172298.287407843286.9100181271172259.95408194843182.743383316
1172273.28740854843086.0767448251172339.95405305842996.910102571
1172404.95402661842741.0768429491172464.12067473842701.076853032
 1172535.7873174842598.5768812551172596.62063196842566.910222206
1172619.95395641842496.9102422041172642.45394922842476.076914372
1172712.45392835842465.2435822251172813.28723065842415.243594077
1172909.95386881842411.0769258791173063.28715607842375.243598687
1173100.78714407842340.243607966 1173336.3232202841945.987291887
1173657.66846917841775.3815411191173909.96956748841490.615143009

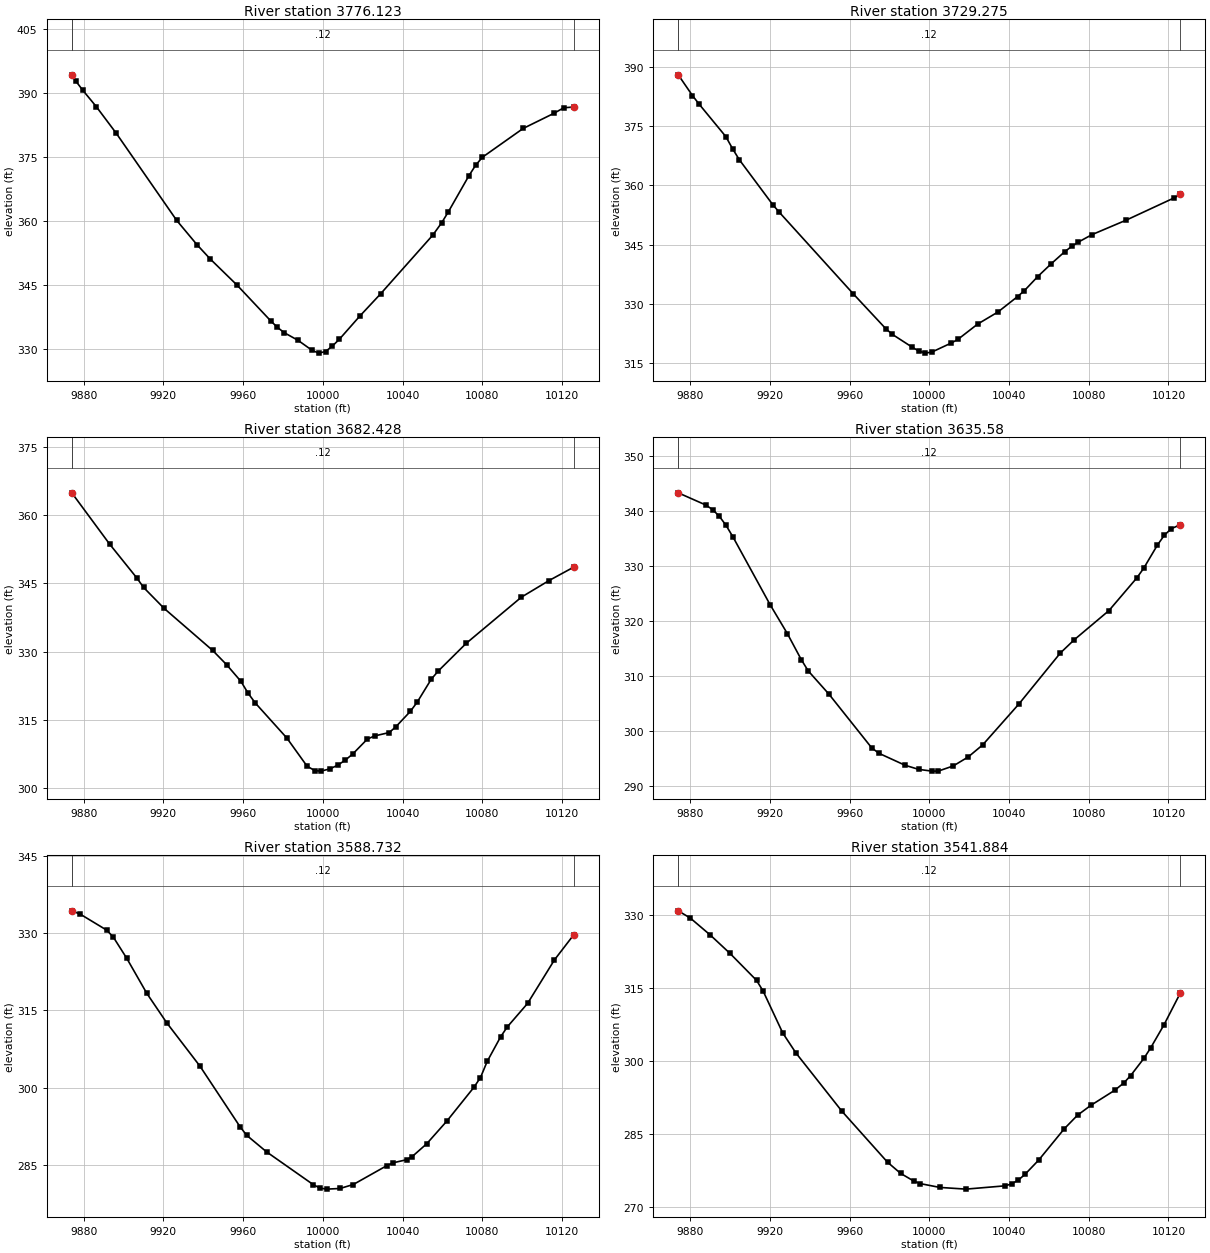
Type RM Length L Ch R = 1 ,3776.123,46.847800,46.847800,46.847800
XS GIS Cut Line= 6
1172700.84349694 844276.611871591172601.36901236844299.709288556
1172579.56190139844306.5918540581172577.68590598844307.285136998
1172553.79978285844315.1858107211172457.67971059844342.167679884
#Sta/Elev= 30
9874.012 394.2239876.183392.67049879.551 390.6039886.287386.79549896.391380.5051
9926.704360.11729936.809354.47649943.545351.08569957.017344.96219973.858336.6164
 9977.25335.0845 9980.69333.83539987.571332.06069994.451329.77459997.892329.0636
10001.37329.435110004.82 330.73410008.28332.295410018.64337.772310028.97342.9274
10055.18356.683710059.64359.573810063.05362.180810073.27 370.55410076.68373.0368
10080.09374.925310100.53381.661810115.88385.183810120.98386.518510125.99386.6778
#Mann= 3 , 0 , 0
9874.012    0.12       09874.012    0.12       010125.99    0.12       0
#XS Ineff= 2 , 0
       0                               0
Bank Sta=9874.012,10125.99
Exp/Cntr=0.3,0.1

Type RM Length L Ch R = 1 ,3729.275,46.847800,46.847800,46.847800
XS GIS Cut Line= 6
1172695.85061729844241.1591316131172606.42323468844260.404393352
1172585.92094635844262.0256947881172556.85086222844260.765988845
1172537.70898715844262.997538531 1172449.6039867844287.567052942
#Sta/Elev= 30
9874.052388.08359881.176382.83239884.532380.64049897.955372.39239901.311369.3317
9904.667366.55969921.447355.15759924.803353.18299961.718332.58979978.247 323.631
9981.538322.20029991.401318.97939994.685318.00519997.969317.461410001.26 317.724
10011.11320.041910014.39320.9569 10024.3324.841310034.47 327.89910044.33331.8222
 10047.7333.301210054.45336.9048 10061.2340.144710067.98343.202510071.41344.5371
10074.83345.653110081.68347.5372 10098.8351.208310122.76356.830510125.96357.7306
#Mann= 3 , 0 , 0
9874.052    0.12       09874.052    0.12       010125.96    0.12       0
#XS Ineff= 2 , 0
       0                               0
Bank Sta=9874.052,10125.96
Exp/Cntr=0.3,0.1

Type RM Length L Ch R = 1 ,3682.428,46.847800,46.847800,46.847800
XS GIS Cut Line= 6
1172677.60993345844171.9295771571172605.17007666844194.652198539
1172579.45486488844206.2944131441172548.83052236 844224.63517533
1172530.35757081844233.6856266671172444.10347408844264.145779888
#Sta/Elev= 30
9874.031364.88479893.024353.6144 9906.68346.16939910.094344.07529920.342339.4999
9944.705330.25339951.724327.11189958.927323.43729962.528320.8289 9966.13 318.688
9981.975310.98229992.081304.81669995.886303.8449    9999303.712610003.57304.1999
10007.55305.037210011.26306.120810015.05307.488810022.35310.752810026.01311.4506
10033.31312.189310036.61  313.44 10043.9316.824610047.41318.897910054.44323.9257
10057.96 325.72810071.95331.795710099.67341.9556 10113.5345.594310125.98348.5671
#Mann= 3 , 0 , 0
9874.031    0.12       09874.031    0.12       010125.98    0.12       0
#XS Ineff= 2 , 0
       0                               0
Bank Sta=9874.031,10125.98
Exp/Cntr=0.3,0.1

Type RM Length L Ch R = 1 , 3635.58,46.847800,46.847800,46.847800
XS GIS Cut Line= 6
1172653.01014042844134.4486381671172580.27151012844156.192744529
1172554.38541558844167.4548643591172519.48870448844186.947685097
1172494.70659687844198.6002425361172418.90285262844225.363314858
#Sta/Elev= 30
9874.028343.28639887.852341.07429891.253340.24429894.654339.02489898.055337.3549
9901.456335.29939920.095322.99189928.824317.69939935.754313.00329939.219310.9661
9949.614 306.7419971.069296.99179974.647296.00249987.865293.81139994.668293.0668
10001.31292.748410004.51292.754410012.04293.692910019.52295.320710026.77297.5037
10044.89304.9046 10065.8314.213610072.76316.609410090.15321.903110104.07327.8088
10107.55329.567110114.51333.822510117.99335.608210121.47 336.77910125.96337.4926
#Mann= 3 , 0 , 0
9874.028    0.12       09874.028    0.12       010125.96    0.12       0
#XS Ineff= 2 , 0
       0                               0
Bank Sta=9874.028,10125.96
Exp/Cntr=0.3,0.1

Type RM Length L Ch R = 1 ,3588.732,46.847800,46.847800,46.847800
XS GIS Cut Line= 5
1172643.78145381 844109.62428344 1172521.1720542844133.912542294
1172519.20849451844134.2925861641172475.45032104844142.738163209
1172397.28199375844161.647586686
#Sta/Elev= 30
9874.008334.31729878.195333.68729891.574330.55939894.918329.18229901.608325.1043
9911.641318.32499921.675312.59099938.398304.15489958.466292.4241 9961.81290.7606
9971.844287.53399995.256 281.1839998.601280.523310001.94280.323110008.63 280.448
10015.31281.220710032.02284.857310035.36285.439310042.04286.027510044.75286.6026
10052.13289.117710062.26293.528210075.76300.041710079.13301.966510082.51305.1097
10089.26309.885810092.64311.821310102.76316.349210116.26324.803310125.99329.6951
#Mann= 3 , 0 , 0
9874.008    0.12       09874.008    0.12       010125.99    0.12       0
#XS Ineff= 2 , 0
       0                               0
Bank Sta=9874.008,10125.99
Exp/Cntr=0.3,0.1

Type RM Length L Ch R = 1 ,3541.884,46.847700,46.847700,46.847700
XS GIS Cut Line= 6
1172642.42811683844079.7291842391172604.22452808844085.563588361
1172571.93840219844088.276957403 1172462.1159596844088.095836316
1172429.46462633844092.3015489681172392.16131112844100.152726625
#Sta/Elev= 30
 9874.03330.88729880.135329.38449890.092325.92469900.048322.12919913.319316.6162
9916.611 314.4259926.488305.79569933.073301.71579956.082 289.785 9979.05279.2813
9985.613276.98829992.175275.42029995.456274.8873 10005.3274.104210018.43273.7542
10038.12274.435110041.41274.844210044.69275.615710047.97276.760610054.93279.7284
10067.77286.153810074.38288.9268   10081290.931910093.04294.041510097.67295.5715
10101.02 297.05310107.73300.616410111.08302.741710117.79307.492910125.97 314.008
#Mann= 3 , 0 , 0
 9874.03    0.12       0 9874.03    0.12       010125.97    0.12       0
#XS Ineff= 2 , 0
       0                               0
Bank Sta=9874.03,10125.97
Exp/Cntr=0.3,0.1

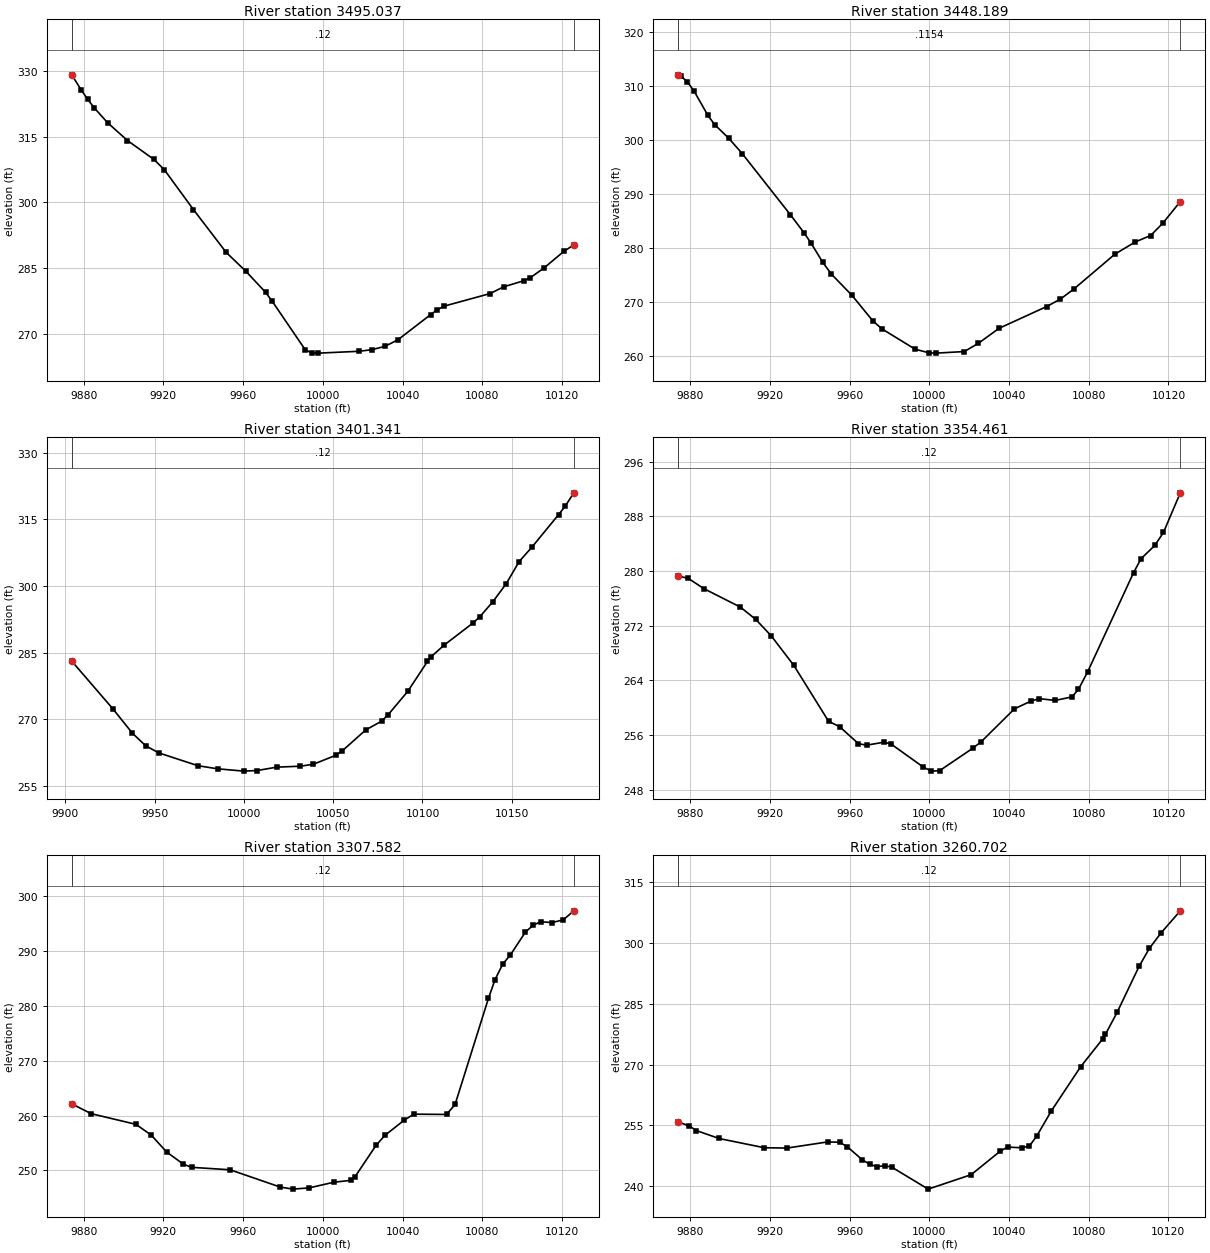
Type RM Length L Ch R = 1 ,3495.037,46.847800,46.847800,46.847800
XS GIS Cut Line= 6
1172650.86572632844036.9614497521172566.88473663844046.815209583
1172540.78162742844045.0382580041172508.19872392844038.298258719
1172480.84004252844038.0427384881172401.94892855844052.951703206
#Sta/Elev= 30
9874.066329.07379878.756325.64169882.079323.46899885.402321.50079892.048318.1401
9902.017314.07669915.309309.7565 9920.49307.41649935.091 298.3249951.529288.5501
9961.393284.24789971.259279.45599974.547277.44059991.113266.37769994.468265.5831
9997.824265.568110018.16265.987610024.48 266.34610031.04267.094410037.61268.5872
10054.08274.361610057.39275.4538 10060.7276.271410083.93279.164710090.67280.6912
10100.78282.082910104.15282.801310110.89284.9824   10121288.830810125.91290.2548
#Mann= 3 , 0 , 0
9874.066    0.12       09874.066    0.12       010125.91    0.12       0
#XS Ineff= 2 , 0
       0                               0
Bank Sta=9874.066,10125.91
Exp/Cntr=0.3,0.1

Type RM Length L Ch R = 1 ,3448.189,46.847800,46.847800,46.847800
XS GIS Cut Line= 6
1172637.47780213843956.5861210441172553.13405401843983.359412044
1172519.14857449843996.6584824671172517.31028446 843997.44632112
1172491.51403788844007.4523961551172398.27492279844035.304294688
#Sta/Elev= 30
9874.014312.02019875.152311.85189878.594310.73669882.036308.97139888.921304.5118
9892.362302.79139899.247300.34459906.132 297.4639930.227   286.29937.111282.8523
9940.553280.99239946.581277.3514 9950.88275.19159961.206271.27219971.745266.5213
9976.294265.06689992.883 261.3269999.942 260.64210003.48260.597410017.55260.8866
10024.59262.395810034.97265.173710058.94 269.21110065.79 270.57810072.64272.4654
10093.18278.890310103.45281.158110111.06282.322610117.15284.581510125.98288.6071
#Mann= 3 , 0 , 0
9874.014  0.1154       09874.014  0.1154       010125.98  0.1154       0
#XS Ineff= 2 , 0
       0                               0
Bank Sta=9874.014,10125.98
Exp/Cntr=0.3,0.1

Type RM Length L Ch R = 1 ,3401.341,46.879700,46.879700,46.879700
XS GIS Cut Line= 3
 1172584.7014069843911.2272213351172462.90148753  843972.4751808
1172333.44557324844037.203137944
#Sta/Elev= 30
 9903.66283.07559926.591272.37849937.608266.85799944.952264.05469952.297262.4338
9974.331259.53569985.348258.837210000.04258.319210007.38258.4541 10018.4259.2137
10031.59259.428510038.89259.863310051.44 261.881 10055.1262.886910068.23267.5972
10077.11269.560110080.78271.021610091.78276.287310102.79283.016210104.91284.1055
10112.25286.726110128.47291.725510132.13 293.09210139.47296.493510146.81300.4748
10154.14305.506610161.48308.846410176.15316.039710179.82317.923910184.73320.9682
#Mann= 3 , 0 , 0
 9903.66    0.12       0 9903.66    0.12       010184.73    0.12       0
#XS Ineff= 2 , 0
       0                               0
Bank Sta=9903.66,10184.73
Exp/Cntr=0.3,0.1

Type RM Length L Ch R = 1 ,3354.461,46.879600,46.879600,46.879600
XS GIS Cut Line= 6
1172581.77792998843844.4925059531172524.98876871843877.670696258
1172470.85546682843917.4892476841172424.55499888843954.062078677
1172400.42920131843969.6350442221172373.08315716843984.710160691
#Sta/Elev= 30
9874.021279.26139879.066278.91029886.858277.41429905.216274.70479912.944272.8975
9920.672270.50849932.032266.16839949.478257.98879955.009257.20129964.452254.7145
9968.527254.49599977.134254.92269980.752254.67679997.053251.2732 10001.1250.6961
10005.17250.758510021.84254.047810026.12255.018110042.75259.814910051.11260.9604
10055.29 261.30310063.18261.047310071.62 261.56210074.87262.683310079.43 265.209
10102.53279.759410106.27281.793810113.19283.740810117.51285.639910125.97291.4347
#Mann= 3 , 0 , 0
9874.021    0.12       09874.021    0.12       010125.97    0.12       0
#XS Ineff= 2 , 0
       0                               0
Bank Sta=9874.021,10125.97
Exp/Cntr=0.3,0.1

Type RM Length L Ch R = 1 ,3307.582,46.879700,46.879700,46.879700
XS GIS Cut Line= 6
 1172535.9227911843806.1531530121172496.60557165843830.041499978
1172469.48512864843851.158251667  1172423.438516843905.998222767
1172402.67317919843925.8823438651172343.06763055843964.338680987
#Sta/Elev= 30
9874.067262.14669883.823260.35819906.224258.42019913.902256.45899921.705253.3549
9930.021251.15289934.179250.57129953.518250.12169978.586246.97689984.996246.5934
9993.274246.828110005.49247.851710014.07248.192910016.06248.797510026.68254.5635
10031.11256.388210040.91259.200610045.66260.271310062.05260.218310066.35 262.042
10083.09281.405910086.38284.809310090.27287.661510094.06289.304910101.64293.4941
10105.43294.730710109.23295.3823   10115295.2356 10120.6295.725910125.93297.3754
#Mann= 3 , 0 , 0
9874.067    0.12       09874.067    0.12       010125.93    0.12       0
#XS Ineff= 2 , 0
       0                               0
Bank Sta=9874.067,10125.93
Exp/Cntr=0.3,0.1

Type RM Length L Ch R = 1 ,3260.702,46.879700,46.879700,46.879700
XS GIS Cut Line= 6
1172519.66990902843790.423627751 1172427.5804734843843.053202374
1172410.42871502843850.9935736931172408.59457493 843851.79102597
1172387.78109485 843861.132149881172296.35277462843906.743097347
#Sta/Elev= 30
9874.032 255.8149879.408254.86869883.187253.68289894.523251.73079917.196249.4512
9928.533249.36129949.003250.88439954.985 250.7979958.763249.75029966.321246.4936
  9970.1245.35999973.879 244.7379977.658245.05449981.379244.59519999.451239.2179
10021.02242.784810035.63248.6025 10039.3249.617210046.63249.4304 10050.3249.8974
10053.96252.3455 10061.3258.565510075.96269.452210086.96276.288210088.39277.4463
10094.29282.913210105.29294.258810110.44298.698910116.29302.515810125.99307.9968
#Mann= 3 , 0 , 0
9874.032    0.12       09874.032    0.12       010125.99    0.12       0
#XS Ineff= 2 , 0
       0                               0
Bank Sta=9874.032,10125.99
Exp/Cntr=0.3,0.1

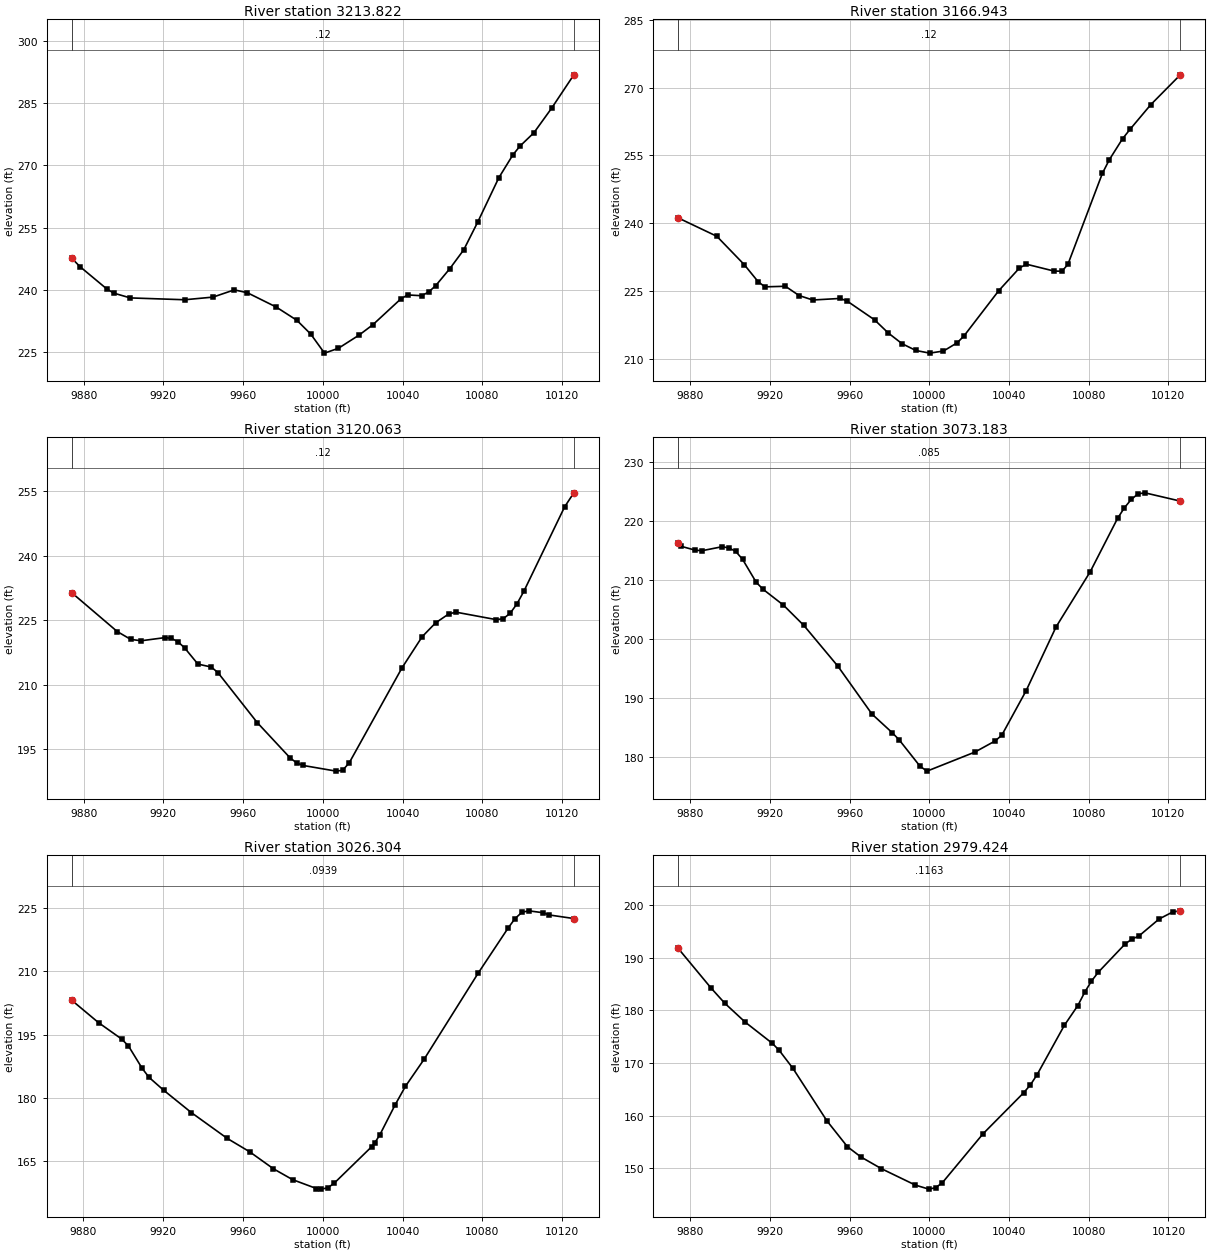
Type RM Length L Ch R = 1 ,3213.822,46.879600,46.879600,46.879600
XS GIS Cut Line= 6
1172511.39960949843760.4250293361172430.20425137843794.750914408
1172395.38960688843806.7678522311172393.46891444843807.325472679
1172361.90156595843818.0165082161172276.52413296843851.373320937
#Sta/Elev= 30
9874.017247.63029878.079245.62749891.477240.27239895.039239.22869903.355238.0678
9930.659237.62369944.907238.26319955.593240.0095 9962.17239.30869976.586235.8791
9986.998232.6714 9993.94229.359810000.85224.766610007.78225.918110018.17229.1004
 10025.1231.594910039.03 237.77310042.55238.7855 10049.6238.595410053.12239.4884
10056.64241.016310063.69245.078810070.73249.653610077.78 256.36810088.34267.0215
10095.39272.520510098.91274.617310105.95277.853510114.82283.756610125.99 291.807
#Mann= 3 , 0 , 0
9874.017    0.12       09874.017    0.12       010125.99    0.12       0
#XS Ineff= 2 , 0
       0                               0
Bank Sta=9874.017,10125.99
Exp/Cntr=0.3,0.1

Type RM Length L Ch R = 1 ,3166.943,46.879700,46.879700,46.879700
XS GIS Cut Line= 5
1172497.38580411843724.9862565441172400.02342466843755.782560234
1172378.35303464843763.1111754211172376.45566806843763.743631009
1172258.18706411 843804.20580234
#Sta/Elev= 30
9874.007241.15799893.382237.09229907.146230.81629914.028227.08779917.469225.9032
9927.792226.03269934.675223.97879941.557222.99099955.321 223.3429958.762222.7616
9972.526218.60729979.429215.68859986.356213.32049993.283211.822910000.21211.2371
10007.14211.703410014.08 213.54510017.54215.105310034.88225.059610045.28230.0808
10048.75230.916210062.62229.397710066.58229.359810069.56230.857710086.89251.0257
10090.36254.027710096.99258.668210100.76260.758910111.17266.2207   10126272.8231
#Mann= 3 , 0 , 0
9874.007    0.12       09874.007    0.12       0   10126    0.12       0
#XS Ineff= 2 , 0
       0                               0
Bank Sta=9874.007,10126
Exp/Cntr=0.3,0.1

Type RM Length L Ch R = 1 ,3120.063,46.879700,46.879700,46.879700
XS GIS Cut Line= 6
  1172487.803007843697.0187031241172449.05957023843707.629179868
1172418.31282741 843713.938194261172367.65553591843718.188081294
 1172323.3533473 843724.121052191172241.54001557843746.447049091
#Sta/Elev= 30
9874.053231.37579896.877222.3706 9903.68220.53979908.935220.23529920.588220.9492
9923.938220.81059927.287220.02159930.636218.60329937.334214.82379944.033214.1365
9947.352212.86139967.106201.24839983.568193.0685 9986.86191.89389990.153191.2924
10006.67 189.97810009.98190.180110013.29191.919810039.77213.965110049.86221.1706
10056.61224.3885 10063.1 226.42410066.72226.879110087.16225.125410090.58225.3696
   10094226.599210097.42228.789210100.84231.666310121.35251.314210125.97254.5645
#Mann= 3 , 0 , 0
9874.053    0.12       09874.053    0.12       010125.97    0.12       0
#XS Ineff= 2 , 0
       0                               0
Bank Sta=9874.053,10125.97
Exp/Cntr=0.3,0.1

Type RM Length L Ch R = 1 ,3073.183,46.879600,46.879600,46.879600
XS GIS Cut Line= 6
1172490.22584912843637.4024568991172385.05175216843668.127913243
1172370.52581832843673.300283103 1172362.4781811843676.388383375
1172322.69856779 843686.177274021172248.67122837843708.766824055
#Sta/Elev= 30
 9874.01216.29569875.542215.69359882.378215.06199885.796214.9474 9896.05215.6312
9899.468215.42339902.886214.83269906.304213.4934 9913.14 209.6149916.558208.4313
9926.812205.74049937.066202.30229954.155195.39869971.245187.29959981.499184.1225
9984.942182.9182 9995.39178.45959998.873 177.64510022.86180.8638   10033182.7416
10036.38183.716910048.59191.245610063.63202.057710080.78211.4007 10094.5220.4296
10097.93222.225710101.36223.629510104.79224.584510108.22224.753410125.99223.3517
#Mann= 3 , 0 , 0
 9874.01   0.085       0 9874.01   0.085       010125.99   0.085       0
#XS Ineff= 2 , 0
       0                               0
Bank Sta=9874.01,10125.99
Exp/Cntr=0.3,0.1

Type RM Length L Ch R = 1 ,3026.304,46.879700,46.879700,46.879700
XS GIS Cut Line= 6
 1172453.4840079843580.7261206811172374.55778622 843610.37021365
1172352.89543209843625.2348081971172330.17978587843649.581127271
1172310.40097635843661.8932786281172231.04896117843690.600421915
#Sta/Elev= 30
9874.124203.14459887.577197.83199899.105  193.979902.551192.31839909.443186.9925
9912.889184.86639920.141 181.8499934.121176.51359952.065 170.4119963.297167.2436
9975.234 163.2099984.824160.63989996.808158.5256    9999158.384410002.41158.6712
10005.66 159.76610024.57168.4699   10026169.336210028.44171.111910036.17178.2754
10041.43182.745510050.79189.160210077.81209.507410092.94220.282210096.39222.5103
10099.84224.001910103.29224.348110110.19223.912510113.64223.360710125.88222.5184
#Mann= 3 , 0 , 0
9874.124  0.0939       09874.124  0.0939       010125.88  0.0939       0
#XS Ineff= 2 , 0
       0                               0
Bank Sta=9874.124,10125.88
Exp/Cntr=0.3,0.1

Type RM Length L Ch R = 1 ,2979.424,19.269700,19.269700,19.269700
XS GIS Cut Line= 5
1172442.28173231843561.3315198551172333.59128364843593.116935969
1172322.18345148843595.8745355231172320.22549066 843596.28244409
1172199.65966318843629.195254324
#Sta/Elev= 30
9874.021191.74079890.547 184.2079897.384181.34459907.638177.75759921.311173.7174
 9924.73172.38899931.566 168.9989948.657159.02579958.912154.13589965.749152.1722
9976.003149.95679993.021146.84819999.767146.083110003.15146.353310006.55147.2912
10026.96156.572610047.36164.359510050.76165.860910054.16167.826710067.77177.1419
10074.57180.912110077.97183.417410081.37 185.53210084.77 187.21110098.37192.6232
10101.77 193.52110105.18194.095110115.38197.337810122.18198.663910125.98198.8775
#Mann= 3 , 0 , 0
9874.021  0.1163       09874.021  0.1163       010125.98  0.1163       0
#XS Ineff= 2 , 0
       0                               0
Bank Sta=9874.021,10125.98
Exp/Cntr=0.3,0.1

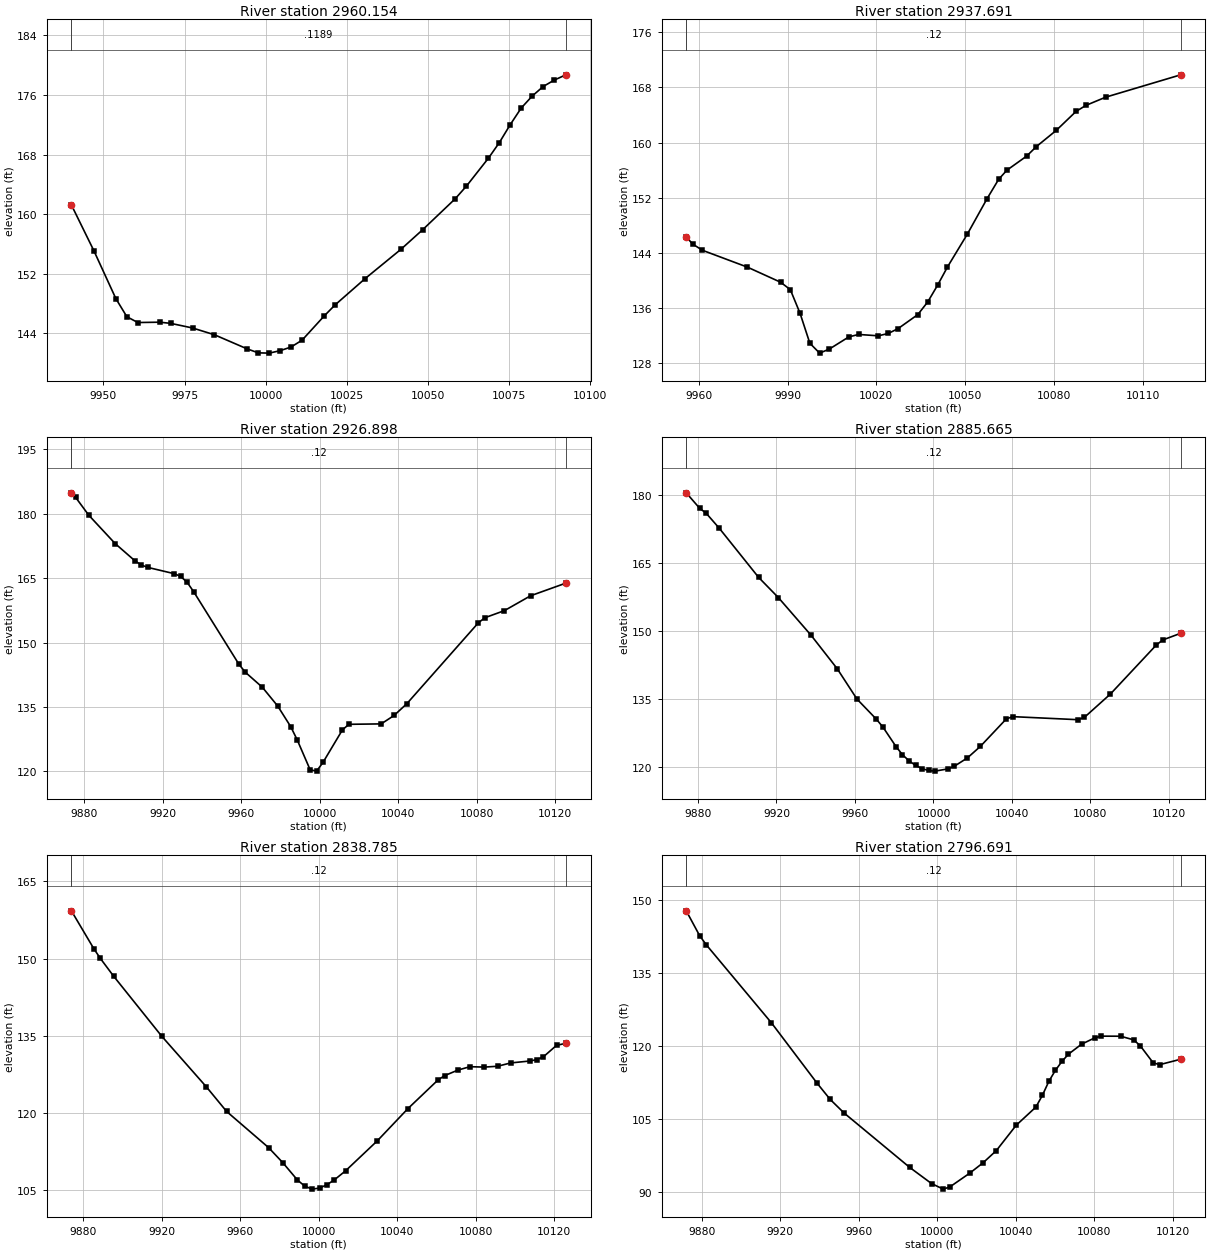
Type RM Length L Ch R = 1 ,2960.154,22.463300,22.463300,22.463300
XS GIS Cut Line= 2
1172374.13337693843563.4506526441172226.04840267843599.457615554
#Sta/Elev= 30
9940.113161.23999947.079155.06089953.832148.65689957.208146.23739960.585145.4562
9967.338145.50169970.714145.34529977.467144.7233 9984.22143.81249994.349141.9083
9997.725141.3871 10001.1141.350110004.48141.682410007.85142.178410011.23143.0943
10017.98146.314310021.36147.808510030.65151.353210041.62 155.25910048.37157.9058
10058.42162.068410061.88163.768910068.63167.502910072.01169.600610075.38172.0182
10078.76174.244110082.14175.847310085.51177.124410088.89177.981310092.51178.6979
#Mann= 3 , 0 , 0
9940.113  0.1189       09940.113  0.1189       010092.51  0.1189       0
#XS Ineff= 2 , 0
       0                               0
Bank Sta=9940.113,10092.51
Exp/Cntr=0.3,0.1

Type RM Length L Ch R = 1 ,2937.691,10.792500,10.792500,10.792500
XS GIS Cut Line= 3
1172356.38346565843560.9149510411172293.49806562843553.814986512
 1172191.5628607  843573.5934591
#Sta/Elev= 30
9955.768146.30839957.924145.27589961.225144.36889976.447141.92029987.639139.7365
 9990.94138.66299994.242135.21719997.544130.883310000.85129.445810004.15130.0396
10010.75131.805910014.05132.154810020.68131.957510024.02132.295510027.36132.9996
10034.04135.037910037.39136.873510040.73139.303710044.07 141.95110050.75146.6887
10057.44151.848110061.37 154.66310064.12155.972810070.81158.024710074.15159.4213
10080.83 161.75710087.52164.512110090.86165.385610097.54166.578310122.89169.8191
#Mann= 3 , 0 , 0
9955.768    0.12       09955.768    0.12       010122.89    0.12       0
#XS Ineff= 2 , 0
       0                               0
Bank Sta=9955.768,10122.89
Exp/Cntr=0.3,0.1

Type RM Length L Ch R = 1 ,2926.898,41.233800,41.233800,41.233800
XS GIS Cut Line= 6
1172438.36755499843534.7098934461172363.61711695843548.144732082
 1172342.3285384843548.5488702461172295.93040245843543.484176085
1172272.84529002843543.232021063 1172188.8867188843555.337008816
#Sta/Elev= 30
9873.498184.88579875.649183.83189882.353 179.6749895.761173.07899905.817169.0707
9909.169168.05629912.521167.50129925.859 166.0579929.169165.41759932.478164.0303
9935.788 161.8619958.874144.93899962.155143.07589970.789139.59339978.614135.2207
9985.221130.43589988.524127.36739995.131120.37899998.434120.056710001.73122.1164
10011.62 129.68810014.92130.964210031.33131.0603 10037.9133.016110044.48135.8005
10080.83154.597310084.16155.789310094.14157.447910107.45160.904910125.42163.8489
#Mann= 3 , 0 , 0
9873.498    0.12       09873.498    0.12       010125.42    0.12       0
#XS Ineff= 2 , 0
       0                               0
Bank Sta=9873.498,10125.42
Exp/Cntr=0.3,0.1

Type RM Length L Ch R = 1 ,2885.665,46.879700,46.879700,46.879700
XS GIS Cut Line= 6
1172446.29607842843485.0904014671172359.49403001843501.365884268
 1172323.2079659 843506.701552931172321.21858232843506.907351289
1172264.33354926843513.5691494051172197.52205915843524.623725643
#Sta/Elev= 30
9874.009180.5176 9880.88177.09289884.218175.99429890.894172.67899910.922161.8527
9920.936157.41859937.626149.10079950.978141.69979960.992135.03849970.949130.5623
9974.265128.83599980.897 124.5589984.213122.7441 9987.53121.41569990.846120.4017
9994.162119.69029997.478119.269210000.78119.130310007.39119.625910010.69120.2239
 10017.3 122.04510023.91124.593210037.12130.648910040.42131.149510073.56130.4768
10076.88130.971210090.18136.137910113.46146.903310116.79148.054110125.99149.5348
#Mann= 3 , 0 , 0
9874.009    0.12       09874.009    0.12       010125.99    0.12       0
#XS Ineff= 2 , 0
       0                               0
Bank Sta=9874.009,10125.99
Exp/Cntr=0.3,0.1

Type RM Length L Ch R = 1 ,2838.785,42.094000,42.094000,42.094000
XS GIS Cut Line= 6
1172424.49432902843424.7917533531172379.40523932843433.991301605
1172346.41988512 843443.682684441172287.95739328843472.946128721
1172264.16507653843482.1686109551172185.55214117843499.508815731
#Sta/Elev= 30
9874.043159.28759885.472  151.92 9888.82150.01879895.517146.59369920.061134.8945
9942.869125.01189953.128 120.2529974.474113.22879981.688110.31379989.198106.9183
9992.953105.71199996.708105.137310000.49105.341410004.23105.998410007.96106.9201
10013.72108.694610029.94114.550110045.42120.772610060.83126.377610064.22127.2217
10071.01 128.307 10077.1128.958610084.47128.882910091.15129.042910097.83129.6902
10107.86 130.076 10111.2130.350210114.54130.888910121.23133.117810125.96133.5043
#Mann= 3 , 0 , 0
9874.043    0.12       09874.043    0.12       010125.96    0.12       0
#XS Ineff= 2 , 0
       0                               0
Bank Sta=9874.043,10125.96
Exp/Cntr=0.3,0.1

Type RM Length L Ch R = 1 ,2796.691,27.171300,27.171300,27.171300
XS GIS Cut Line= 6
1172410.17087536843401.222766517  1172330.890002843414.600713845
1172287.68777749843425.5566502071172285.91226845843426.477284588
 1172240.7574729843437.6066422121172163.23754922843449.656431603
#Sta/Elev= 30
9872.033147.70829878.845142.61489882.172140.75769915.445124.68289938.735112.2545
9945.389108.93359952.435106.15389985.88494.965249997.00591.6454210002.9790.49875
10006.3590.9526710016.4993.7847710023.2495.90492   1003098.4064810040.14103.6232
10050.19107.373610053.51 109.79610056.83112.690710060.15114.933810063.47116.7607
10066.79118.247110073.43120.289910080.07121.574710083.39121.947110093.36121.9299
   10100121.184610103.32119.984310109.96116.451910113.28116.089210123.96117.1984
#Mann= 3 , 0 , 0
9872.033    0.12       09872.033    0.12       010123.96    0.12       0
#XS Ineff= 2 , 0
       0                               0
Bank Sta=9872.033,10123.96
Exp/Cntr=0.3,0.1

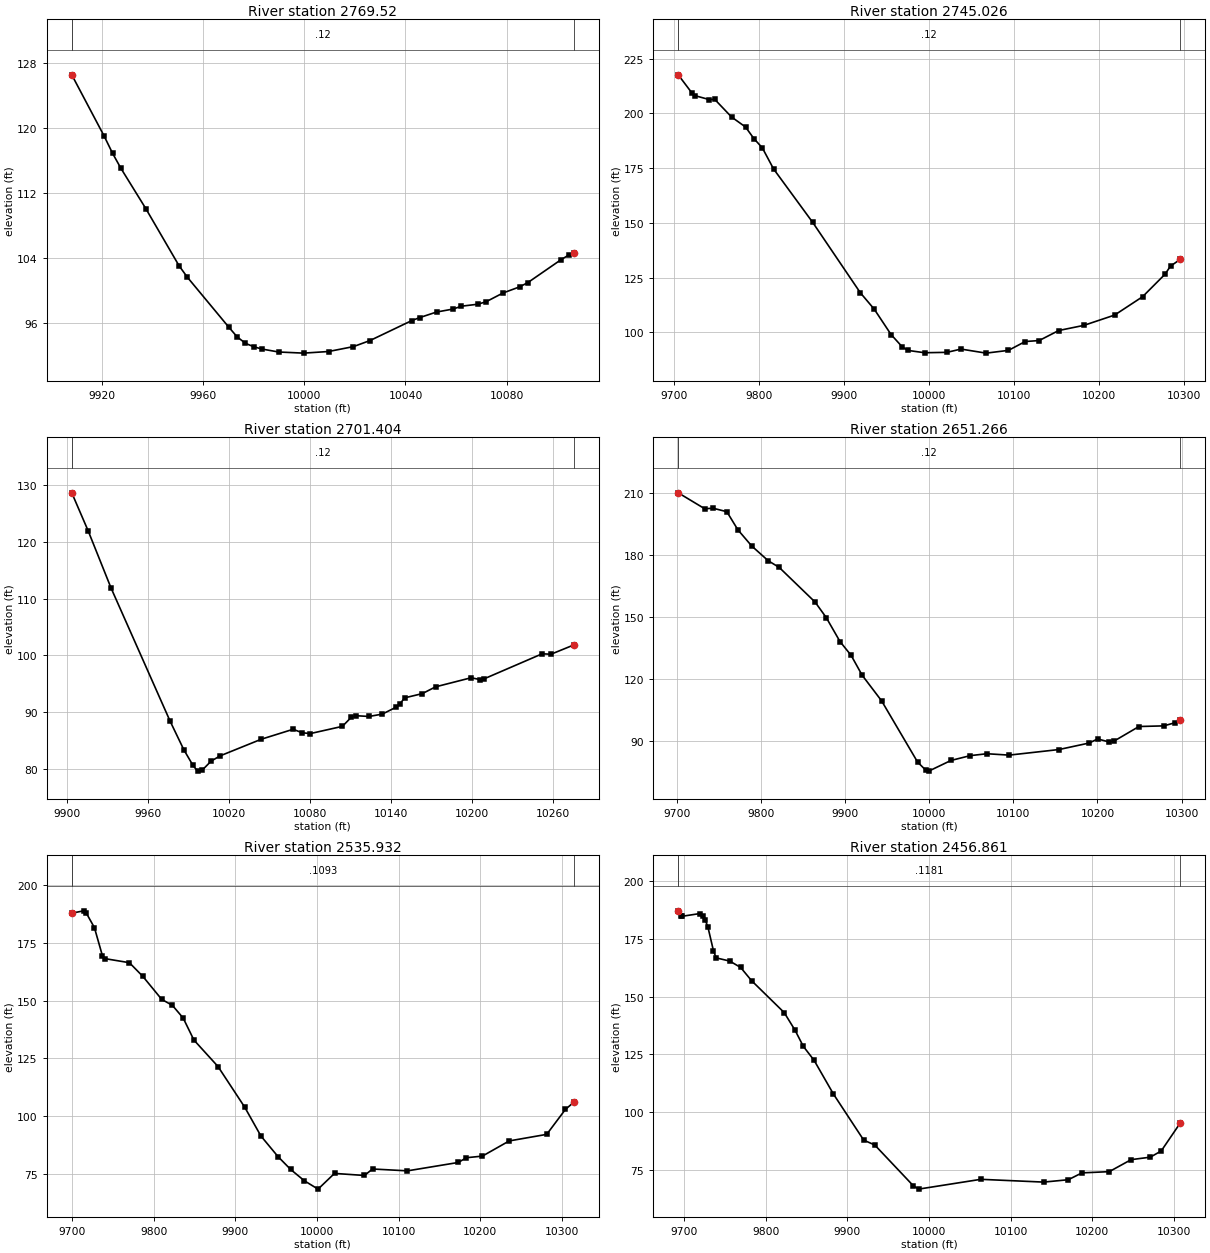
Type RM Length L Ch R = 1 , 2769.52,24.494000,24.494000,24.494000
XS GIS Cut Line= 2
1172373.62623659843397.1086267681172175.33437037843403.701450959
#Sta/Elev= 30
9908.137126.50779920.968118.9485 9924.25116.85259927.533115.01129937.381110.0495
9950.512103.01989953.794101.60189970.20795.44011 9973.4994.256119976.77393.45941
9980.05593.039969983.338 92.75369989.90392.392219999.75192.25404 10009.692.45268
10019.4593.0571410026.0193.8054410042.4396.2504710045.71 96.635210052.2797.31108
10058.8497.6808110062.1298.0299410068.69 98.276410071.97 98.594510078.5399.65466
 10085.1100.408710088.38100.938710101.51103.7623 10104.8104.377710106.54104.5462
#Mann= 3 , 0 , 0
9908.137    0.12       09908.137    0.12       010106.54    0.12       0
#XS Ineff= 2 , 0
       0                10049.25       0
Bank Sta=9908.137,10106.54
Exp/Cntr=0.3,0.1

Type RM Length L Ch R = 1 ,2745.026,43.621600,43.621600,43.621600
XS GIS Cut Line= 6
1172577.42698154843359.2311196321172355.81361896843378.531463723
1172320.87144316843378.6991955171172251.92559254843373.185734283
1172212.34527029843372.3119404321171988.38708978843385.097721405
#Sta/Elev= 30
9704.767217.59679721.323209.06849724.616208.05799741.083206.31569747.669206.3917
9767.429198.34549783.895193.76419793.775188.46089803.654184.24729816.827174.6421
9862.933150.17549918.918118.04849935.354110.50479955.03998.970949968.18193.33345
9974.76391.714639994.50890.6457610020.8490.8290810037.2892.3201410066.82 90.4679
 10093.191.7256310112.8295.7644310129.2596.2148510152.25100.800210181.83103.1479
10217.97107.850410250.84116.229410277.13126.4562 10283.7130.200410295.24 133.331
#Mann= 3 , 0 , 0
9704.767    0.12       09704.767    0.12       010295.24    0.12       0
#XS Ineff= 2 , 0
       0                10049.27       0
Bank Sta=9704.767,10295.24
Exp/Cntr=0.3,0.1

Type RM Length L Ch R = 1 ,2701.404,50.137700,50.137700,50.137700
XS GIS Cut Line= 3
1172385.79760432843355.0159799751172213.87703493843314.951894492
  1172019.135151843324.587560609
#Sta/Elev= 30
9903.833128.67679916.022121.93219932.866111.8982 9976.6688.346019986.766 83.3284
9993.50380.581869996.87279.5624810000.2479.7077110006.9881.3371510013.7282.26841
10044.0385.1898910067.6286.9477610074.3586.3313210080.3686.1908710104.0787.46286
10110.6489.0608510113.9289.3468110123.7889.2098310133.6389.6277810143.48 90.8057
10146.7791.4485710150.0592.4881310163.1993.2399910173.0594.4401510199.3396.04086
 10205.995.7205110209.1895.8737610251.88100.267110258.45100.195210275.34101.8351
#Mann= 3 , 0 , 0
9903.833    0.12       09903.833    0.12       010275.34    0.12       0
#XS Ineff= 2 , 0
       0                10058.16       0
Bank Sta=9903.833,10275.34
Exp/Cntr=0.3,0.1

Type RM Length L Ch R = 1 ,2651.266,115.333900,115.333900,115.333900
XS GIS Cut Line= 6
1172595.76368046843271.457873458 1172521.8103723843269.837456858
1172437.07249318843271.5369061061172369.64904111843276.242676115
1172183.18653597843295.1290259931171999.94286981843301.573210625
#Sta/Elev= 30
9701.442210.09099732.999202.37599742.844202.65079759.252200.95639772.378192.2075
9788.786184.39319808.475177.23529821.601173.98569864.269157.21589877.425149.7765
9893.869138.12289907.024131.49289920.179121.85399943.253109.49669986.15179.82355
 9996.0575.857569999.35275.4673310025.77 80.629910048.8782.9726810068.6483.87901
10094.9883.2111210154.1685.90381 10190.3 89.074410200.1591.0406210213.2889.64733
10219.8490.0157510249.3897.0495510278.9197.3579910292.0498.8534810298.57100.4388
#Mann= 3 , 0 , 0
9701.442    0.12       09701.442    0.12       010298.57    0.12       0
#XS Ineff= 2 , 0
       0                10063.82       0
Bank Sta=9701.442,10298.57
Exp/Cntr=0.3,0.1

Type RM Length L Ch R = 1 ,2535.932,79.071600,79.071600,79.071600
XS GIS Cut Line= 6
1172558.99333997 843177.983462591172368.58936539843162.088820382
1172307.10718229843166.4772506671172220.26970558843185.402456264
1172162.76992994843191.8766493891171947.01949321843186.493558263
#Sta/Elev= 30
9699.444187.89139713.991188.90639717.291187.90359727.191181.63849737.091169.3535
 9740.39168.17469770.089166.42599786.589160.48279809.688150.53329822.873147.9082
9836.008142.43929849.143132.92049878.697121.43299911.528103.76529931.28191.33062
 9952.2882.382679967.82176.800129984.59271.9083310001.3668.2892510021.5475.10802
10058.2174.2021710068.1277.0168110110.9676.21173 10173.379.8474710183.1481.89679
10202.8482.6022210235.6989.1791510281.6892.0242810304.67102.871310314.93105.9612
#Mann= 3 , 0 , 0
9699.444  0.1093       09699.444  0.1093       010314.93  0.1093       0
#XS Ineff= 2 , 0
       0                10031.41       0
Bank Sta=9699.444,10314.93
Exp/Cntr=0.3,0.1

Type RM Length L Ch R = 1 ,2456.861,96.799100,96.799100,96.799100
XS GIS Cut Line= 6
1172573.82647799843159.2703095761172409.73593934843128.742869399
1172300.73519898843102.0980712051172271.28548254 843098.69280691
1172238.87260343843094.5483582191171970.38859717843039.320422804
#Sta/Elev= 30
9692.587187.08379695.689184.9329 9697.71184.74389719.049185.89569722.386184.8921
9725.723183.1199 9729.06179.94259735.735169.85649739.072166.72299755.757165.3466
9769.106162.57039782.454  156.88  9822.5 143.0569835.849135.3928 9845.86128.4879
9859.208122.36349882.847107.80959919.99987.858959933.508 85.76839980.59668.19553
9987.20566.6644210063.62 70.907410140.6669.7054110170.8170.7299310187.5673.69751
10221.0574.2281710247.8579.42191 10271.380.4894610284.6983.1636910308.1495.30724
#Mann= 3 , 0 , 0
9692.587  0.1181       09692.587  0.1181       010308.14  0.1181       0
#XS Ineff= 2 , 0
       0                10021.38       0
Bank Sta=9692.587,10308.14
Exp/Cntr=0.3,0.1