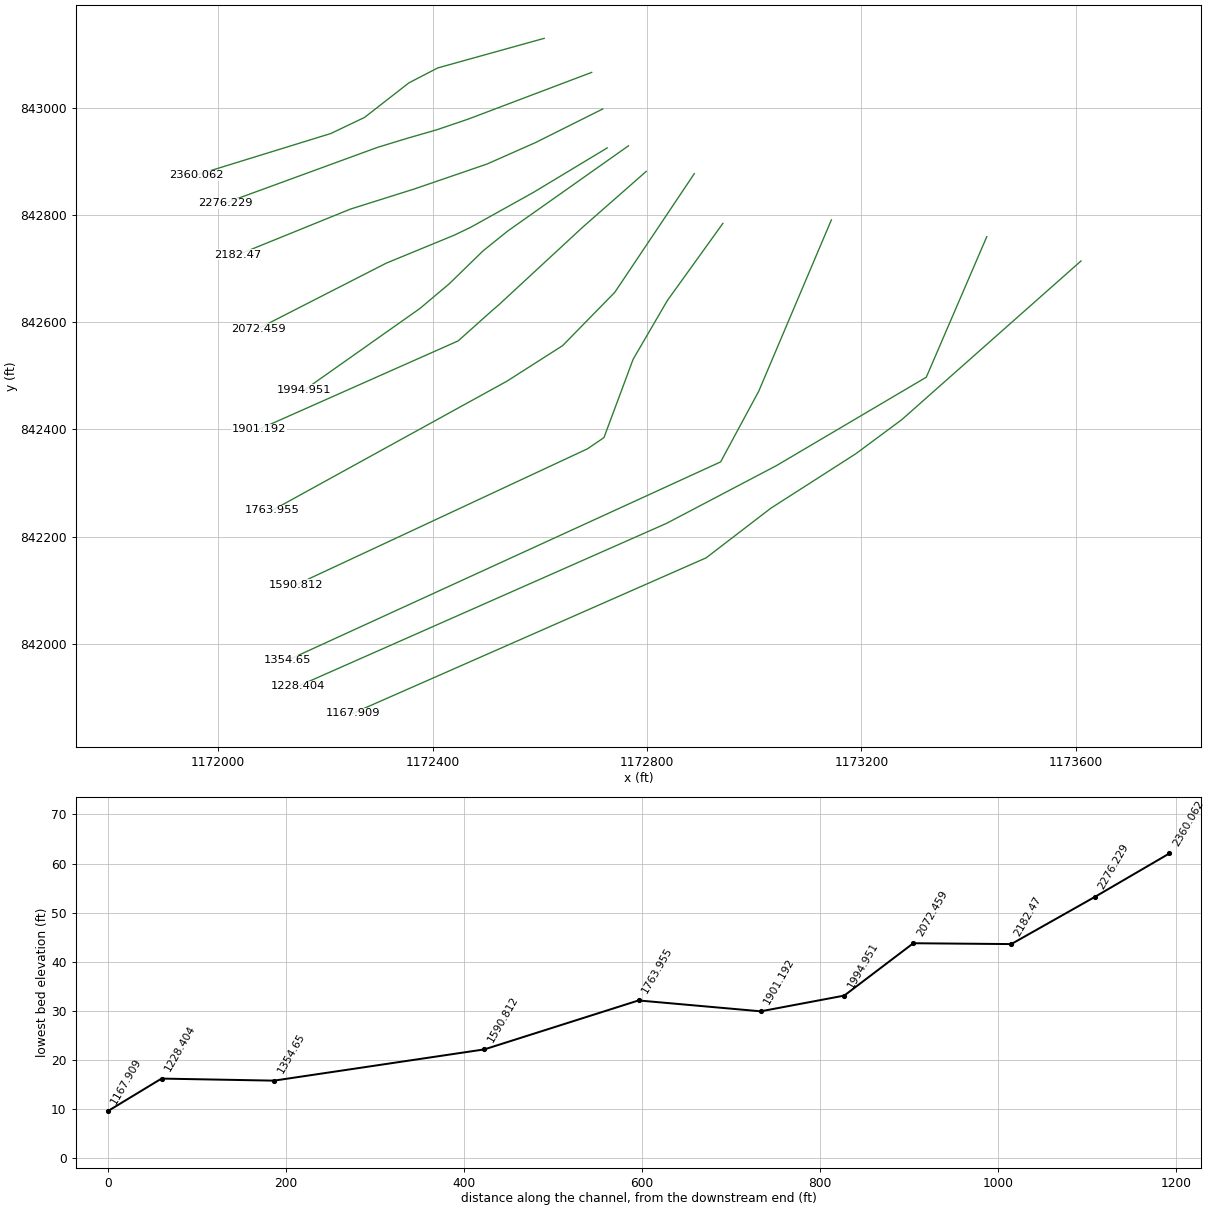
HEC-RAS study 87_ras.prj: 87

--- 87_ras.g01 (geometry) --- (continued)

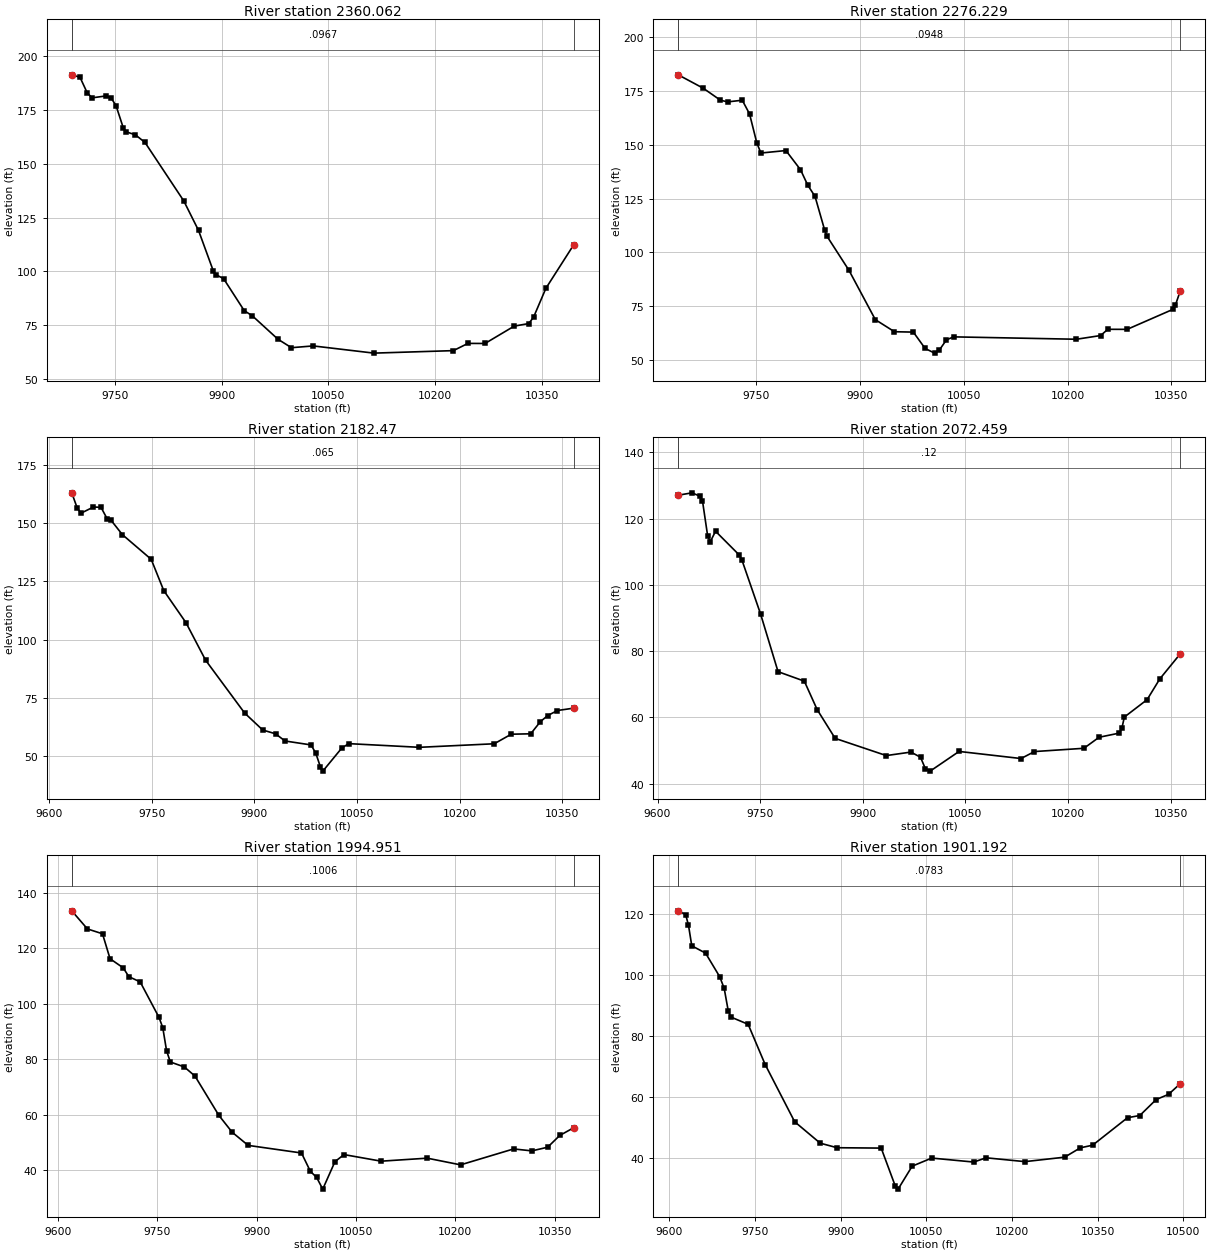
Type RM Length L Ch R = 1 ,2360.062,83.832700,83.832700,83.832700
XS GIS Cut Line= 6
1172608.21673235 843129.672127531172409.62988105843074.457390428
1172355.95227414843046.6917881671172273.11652419842982.178719491
1172210.16686264842952.142793417 1171958.9266524842874.594431505
#Sta/Elev= 30
9689.744191.35049701.273190.2211 9711.41183.00469718.168180.65329738.443181.5775
9745.201180.49849751.959176.94779762.096166.67069765.475164.93469778.992163.4928
9792.508 159.9499847.002132.76899867.678119.0826 9888.64100.07399892.13398.48212
9902.83796.688789931.86281.798869943.29479.38016 9979.1768.536479998.14864.58893
10028.6365.4181510113.8662.0685710225.4663.2302910245.9666.5895810269.8866.55182
10310.8974.61989 10331.475.8145110338.2378.9028610355.3292.1639910394.59112.4911
#Mann= 3 , 0 , 0
9689.744  0.0967       09689.744  0.0967       010394.59  0.0967       0
#XS Ineff= 2 , 0
       0                10054.94       0
Bank Sta=9689.744,10394.59
Exp/Cntr=0.3,0.1

Type RM Length L Ch R = 1 ,2276.229,93.759300,93.759300,93.759300
XS GIS Cut Line= 6
1172696.75956038843066.1370067631172466.25184512842978.906966669
1172407.84660511842959.0704513561172354.09408789842943.589060949
1172297.43538525842926.3401877281172012.99809633 842822.34803066
#Sta/Elev= 30
 9636.92182.55219673.058 176.3329697.956170.7479 9708.48169.97919729.527170.7472
9740.051164.38889750.575150.89529756.485146.20449792.669 147.3549813.717 138.469
 9824.24131.26699834.764126.03479848.796110.27959852.304107.40759883.86991.67738
9921.98268.758239949.63463.144059976.94962.963979994.02255.3601310007.71 53.1948
10014.5654.6236810024.8559.3673310035.1460.7564410212.8359.6472410247.7661.36526
10258.24 64.268910286.1964.2443410352.5673.5630210356.0575.5822710363.0882.15277
#Mann= 3 , 0 , 0
 9636.92  0.0948       0 9636.92  0.0948       010363.08  0.0948       0
#XS Ineff= 2 , 0
       0                10063.63       0
Bank Sta=9636.92,10363.08
Exp/Cntr=0.3,0.1

Type RM Length L Ch R = 1 , 2182.47,110.010600,110.010600,110.010600
XS GIS Cut Line= 6
1172717.27290421 842997.833496121172591.48932188842934.973644884
1172501.76342286842895.2740503711172366.16167719842848.741994843
1172246.40099707842811.0033691781172036.89111894842725.931148135
#Sta/Elev= 30
9633.088163.04599641.011156.54369646.483154.29439664.821156.95979675.825156.8191
9685.045151.76849690.495151.26959707.063145.09759749.179134.50579767.517121.0978
9799.941107.34329828.64291.229989885.69968.536699912.13461.245389930.95359.60368
9944.768 56.52589982.76154.836429989.66951.359869996.57745.3347410000.0443.58559
10027.6553.4580910037.9255.3855610141.2553.8077710250.5555.3272110275.4459.43509
10303.8959.6076310318.1164.8512410328.7867.44383   1034369.6066510366.9370.62452
#Mann= 3 , 0 , 0
9633.088   0.065       09633.088   0.065       010366.93   0.065       0
#XS Ineff= 2 , 0
       0                10065.41       0
Bank Sta=9633.088,10366.93
Exp/Cntr=0.3,0.1

Type RM Length L Ch R = 1 ,2072.459,77.508100,77.508100,77.508100
XS GIS Cut Line= 6
1172725.74349053842925.2287790111172587.75820446 842842.08211972
 1172471.5054795842777.4017221931172439.99179598842762.302838186
1172313.73913318842710.3785817791172074.93625623 842588.31345742
#Sta/Elev= 30
9630.242127.09519650.291127.81579661.782126.82279665.612125.48279673.273114.7534
9677.104113.04199684.764 116.2159719.238109.07079723.069107.6749  9750.791.14523
9776.12773.79678 9814.5370.936419833.30262.338889859.58353.652719934.35348.45451
9970.32549.510269984.35647.949999991.37244.524919998.43343.7583510040.7149.70539
10131.2547.5613310150.9349.6682310223.1850.6553710245.3553.9859110274.9155.24095
 10278.656.66619 10282.360.0877710315.56 65.348810334.0371.5909110364.0879.20194
#Mann= 3 , 0 , 0
9630.242    0.12       09630.242    0.12       010364.08    0.12       0
#XS Ineff= 2 , 0
       0                10059.74       0
Bank Sta=9630.242,10364.08
Exp/Cntr=0.3,0.1

Type RM Length L Ch R = 1 ,1994.951,93.759300,93.759300,93.759300
XS GIS Cut Line= 6
1172765.40727951842929.1890025961172539.84194165842769.972744167
1172494.09709847 842733.150108681172430.96875261842671.662838002
1172376.12622297842625.5630604221172160.86781858842473.713457161
#Sta/Elev= 30
 9620.96133.51149644.609126.97279667.366125.23289678.744116.2225 9698.56112.9492
9707.191 109.7519724.259107.86139752.70595.048279758.39591.318259764.08483.03355
9769.77378.965219790.92477.172699806.98773.880579843.129 59.67929863.20953.59988
9887.30348.867979967.80146.128419981.22939.507619990.66837.316199999.91233.08542
 10018.443.0252210032.0545.5467910088.1143.1716410157.6444.2569510208.0141.84527
 10288.147.5918610315.6546.8866310339.5148.2122810357.7452.4470210379.0555.26688
#Mann= 3 , 0 , 0
 9620.96  0.1006       0 9620.96  0.1006       010379.05  0.1006       0
#XS Ineff= 2 , 0
       0                10072.46       0
Bank Sta=9620.96,10379.05
Exp/Cntr=0.3,0.1

Type RM Length L Ch R = 1 ,1901.192,137.237000,137.237000,137.237000
XS GIS Cut Line= 6
1172798.55691981842881.4672839791172679.92419654842777.308209911
1172523.17515442842632.2460029421172512.70997113842623.344375223
1172447.71679741 842565.267184661172076.18901965842400.336629108
#Sta/Elev= 30
9615.819121.09679628.802119.87769633.775116.34569639.515109.63189663.611107.2454
9688.47499.482399696.27395.670469703.39288.259679708.364  86.252  9738.283.90085
9768.03670.69656 9819.5951.972369864.29144.949539893.78643.451929971.07143.32871
9995.59730.9585110000.6729.88054 10025.3 37.404710059.5240.06048   1013338.75459
10154.7340.1464710222.7438.89244 10292.240.3540810319.6643.41627 10341.244.28209
10402.2253.2866810423.7654.0120710452.4759.2522110474.0160.9395410494.6564.45667
#Mann= 3 , 0 , 0
9615.819  0.0783       09615.819  0.0783       010494.65  0.0783       0
#XS Ineff= 2 , 0
       0                 10069.7       0
Bank Sta=9615.819,10494.65
Exp/Cntr=0.3,0.1

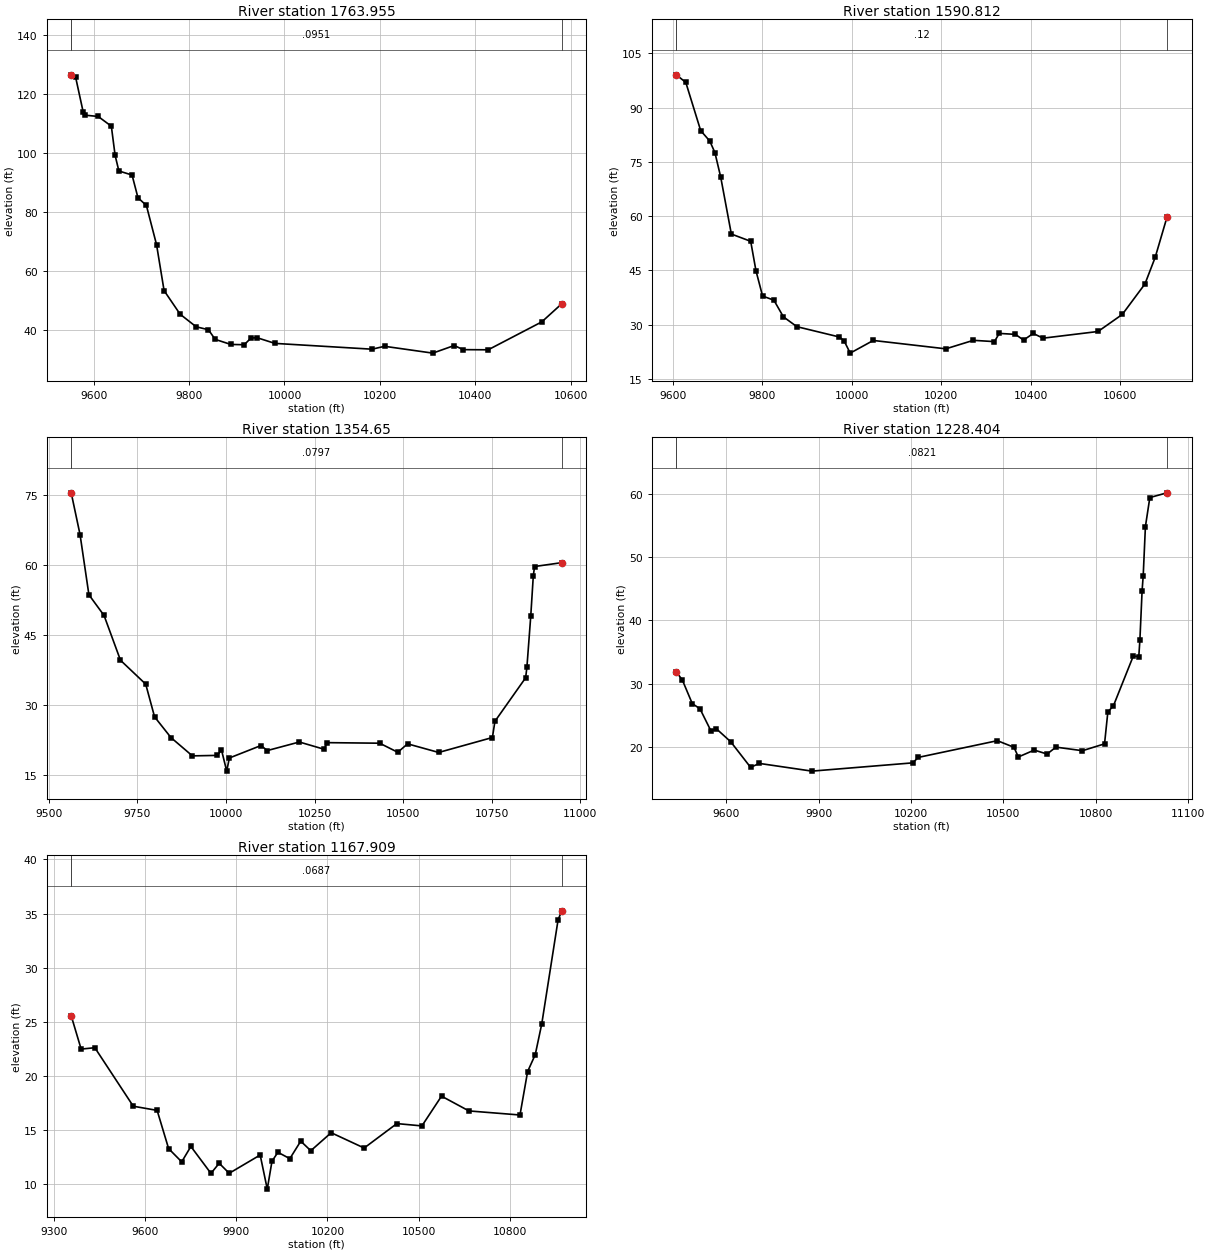
Type RM Length L Ch R = 1 ,1763.955,173.143200,173.143200,173.143200
XS GIS Cut Line= 5
1172888.17267269842877.1884391161172739.98663744842656.015252188
1172642.67043522842556.4873180841172538.71903735842490.135361984
1172100.79612726842249.056588247
#Sta/Elev= 30
9552.927126.48239562.037125.79699577.833 114.0319581.782112.80149609.426112.3666
9637.071109.06369644.96999.171149652.86793.872439680.51192.498769692.87184.80311
9710.55482.17263 9731.8568.880069747.64753.300139781.28545.293839814.78241.03994
9840.62540.026039854.70336.763229887.49135.04427 9915.7134.943559929.78837.21273
9942.55337.321319980.04235.3973710183.6533.4284510209.8734.4114810310.9832.09568
10355.9334.6817810374.6533.2759410427.0833.2247710539.4442.6921410581.5748.87085
#Mann= 3 , 0 , 0
9552.927  0.0951       09552.927  0.0951       010581.57  0.0951       0
#XS Ineff= 2 , 0
       09929.749        10055.12       0
Bank Sta=9552.927,10581.57
Exp/Cntr=0.3,0.1

Type RM Length L Ch R = 1 ,1590.812,236.161400,236.161400,236.161400
XS GIS Cut Line= 6
1172941.54908073842784.4761722391172837.90955269842640.474421203
1172774.05121261842530.9029038851172719.72760084842384.940040275
1172689.11680445842364.0666454581172145.58773357842110.419745713
#Sta/Elev= 30
9607.87799.071469629.11196.968929662.37783.645989682.72380.756619694.18477.56178
9707.13870.807959730.92855.04713 9774.2253.038359786.01244.898459800.76837.91026
9826.12336.752749847.36132.15064 9877.5629.430469972.52826.581169983.063 25.5281
9996.72522.1174210048.3725.6225910210.63 23.306510272.18 25.657910319.2425.29884
 10330.127.5718110366.3127.3008510384.4125.7257510406.1427.5628610427.8626.24862
10550.9628.0990110605.2632.8196210655.9541.2540910678.77 48.587910705.18 59.7187
#Mann= 3 , 0 , 0
9607.877    0.12       09607.877    0.12       010705.18    0.12       0
#XS Ineff= 2 , 0
       09919.741           10036       0
Bank Sta=9607.877,10705.18
Exp/Cntr=0.3,0.1

Type RM Length L Ch R = 1 , 1354.65,126.245700,126.245700,126.245700
XS GIS Cut Line= 4
1173143.89735298842790.9616290941173008.48068632842471.517184676
1172937.30013074842339.5727402291172130.00846411841969.781073542
#Sta/Elev= 30
9562.88375.560729587.91666.56057 9612.86 53.65239655.62149.200619701.946 39.5808
9773.21534.438019798.15927.416169844.48422.958959904.907  19.029 9975.67 19.1322
9986.85420.3652510001.7615.7506510009.22 18.571510098.4421.2500810116.48 20.1715
 10206.722.0093310275.9520.4696710286.0921.8709610433.51 21.752310484.5619.80241
10512.2921.6147310600.0419.76234 10751.622.9750510758.8226.4645510845.43 35.8081
10849.04 38.091110859.8649.0349410867.0857.7407310870.6959.7253810947.7260.55702
#Mann= 3 , 0 , 0
9562.883  0.0797       09562.883  0.0797       010947.72  0.0797       0
#XS Ineff= 2 , 0
       09904.363        10050.65       0
Bank Sta=9562.883,10947.72
Exp/Cntr=0.3,0.1

Type RM Length L Ch R = 1 ,1228.404,60.495500,60.495500,60.495500
XS GIS Cut Line= 5
1173433.82790855842759.7116291081173320.98068631842497.558851317
1173041.46679744842332.6282957791172836.60568631842224.989406899
1172149.10568634841921.169962466
#Sta/Elev= 30
9438.04831.843739457.69330.54453 9489.8426.834619514.84326.014519550.56222.51261
9568.42122.842429614.85620.79699 9679.1516.768939707.72517.385719878.35816.16877
10205.3917.4730910223.9218.3398410480.3820.9769310534.1819.9340810548.5318.40441
10600.1619.4939410641.7918.8661110670.4819.9595910756.5719.3933610828.3120.47742
10839.0725.51895   1085726.4664810921.5734.32951 10939.534.2605810943.0936.85403
10950.2644.6637510953.8547.0213110961.0254.7875110975.3759.3659311031.0660.11023
#Mann= 3 , 0 , 0
9438.048  0.0821       09438.048  0.0821       011031.06  0.0821       0
#XS Ineff= 2 , 0
       0 9903.19        10110.18       0
Bank Sta=9438.048,11031.06
Exp/Cntr=0.3,0.1

Type RM Length L Ch R = 1 ,1167.909,0.000000,0.000000,0.000000
XS GIS Cut Line= 6
1173609.51398492842714.3282808211173275.33810142 842418.41354917
1173189.42521346842354.7129698251173030.87617013  842253.0801218
1172910.28999138842160.5873134581172251.10135156841870.458980069
#Sta/Elev= 30
9357.16625.543269389.84222.462069434.92622.590199561.38317.179259639.80116.79484
9677.58513.260459720.65712.035649750.807 13.45899816.84910.970589843.96111.90578
9876.89310.979229978.77212.6690810002.089.51367210017.6212.0943310037.1112.91946
 10076.312.33136 10112.213.9494710145.2513.0658810212.3414.7302810320.7713.31437
 10428.315.5740310510.7515.3594210575.2718.1112710665.3616.7451710833.3616.36858
10858.4520.3845310883.5421.9481110905.0524.8061710958.8234.4417410971.14 35.2475
#Mann= 3 , 0 , 0
9357.166  0.0687       09357.166  0.0687       010971.14  0.0687       0
#XS Ineff= 2 , 0
       09874.807        10093.69       0
Bank Sta=9357.166,10971.14
Exp/Cntr=0.3,0.1